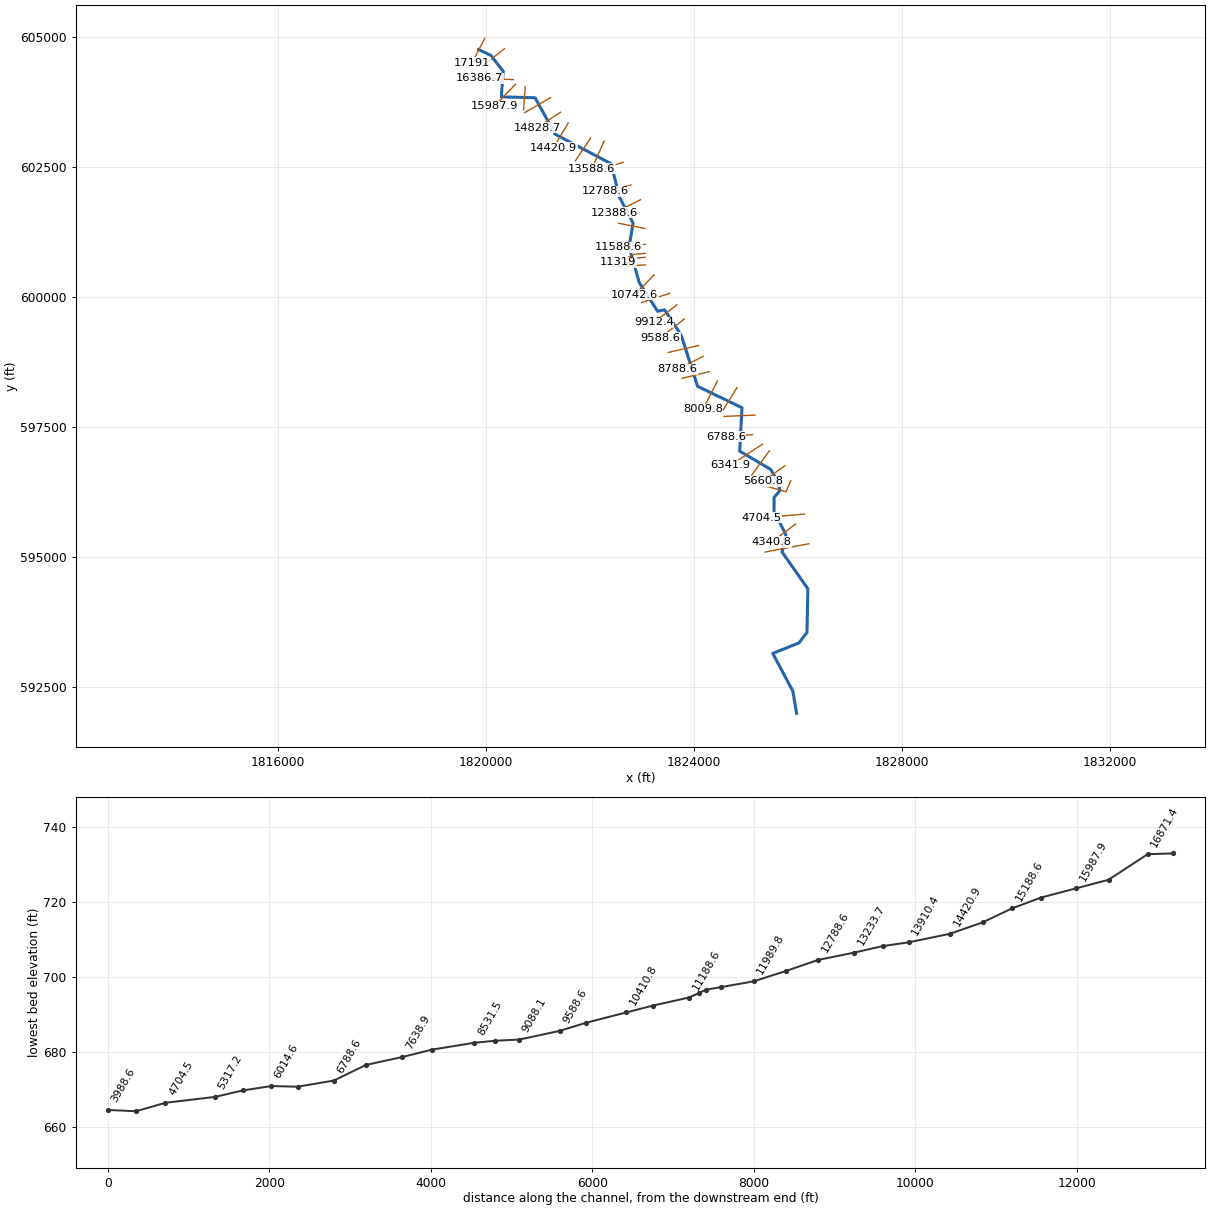
--- WolfCreek.prj (project) ---

Proj Title=WolfCreek
Current Plan=p01
Default Exp/Contr=0,0
English Units
Geom File=g01
Flow File=f01
Plan File=p01
BEGIN DESCRIPTION:
AMEC Environment & Infrastructure, 2013
Projection: NAD 1983 State Plane West Virginia South FIPS 4702 (US Feet)
Vertical Datum: NAVD 1988
END DESCRIPTION:
DSS Export Rating Curves= 0
DSS Export Rating Curve Sorted= 0
DSS Export Volume Flow Curves= 0
DXF OffsetX= 0
DXF OffsetY= 0
DXF ScaleX= 0
DXF ScaleY= 0

--- WolfCreek.p01 (plan) ---

Plan Title=Floodplain
Program Version=4.00
Geom File=g01
Flow File=f01
K Sum by GR=0
Std Step Tol=0.01
Critical Tol=0.01
Num of Std Step Trials=20
Max Error Tol=0.3
Flow Tol Ratio=0.001
Split Flow NTrial=30
Split Flow Tol=0.02
Split Flow Ratio=0.02
Log Output Level=0
Friction Slope Method=1
Unsteady Friction Slope Method=2
Unsteady Bridges Friction Slope Method=1
Global Log Level=0
CheckData=False
Run HTab=0
Run UNet=0
Run PostProcess=0
UNET Theta=0
UNET Theta Warmup=0
UNET ZTol=0
UNET ZSATol=0
UNET MxIter=0
UNET MaxInSteps=0
UNET DtIC=0
UNET DtMin=0
UNET MaxCRTS=0
UNET WFStab=0
UNET SFStab=0
UNET WFX=0
UNET SFX=0
UNET DSS MLevel=0
UNET DZMax Abort=0
UNET Convert EG Bridges=0
UNET Use Existing IB Tables=0
UNET Froude Limit=0
UNET Froude Power=0
Write IC File=0
Echo Input=False
Echo Output=False
Write Detailed=0

--- WolfCreek.f01 (steady flow) ---

Flow Title=NFF Regression Equation
Program Version=4.00
Number of Profiles=1
Profile Names=P100yr
River Rch & RM=WolfCreek,Main      ,17191
897.6510
River Rch & RM=WolfCreek,Main      ,16386.7
962.1133
River Rch & RM=WolfCreek,Main      ,15548.4
1038.482
River Rch & RM=WolfCreek,Main      ,13233.7
1130.957
River Rch & RM=WolfCreek,Main      ,10742.6
1434.570
River Rch & RM=WolfCreek,Main      ,10742.6
1214.762
River Rch & RM=WolfCreek,Main      ,7638.9
1525.833
River Rch & RM=WolfCreek,Main      ,4340.8
1694.353
River Rch & RM=WolfCreek,Main      ,583.6
1829.858
River Rch & RM=WolfCreek,Main      ,258.1
1831.970
Boundary for River Rch & Prof#=WolfCreek,Main      ,1
Up Type=0
Dn Type=3
Dn Slope=0.001728

--- WolfCreek.g01 (geometry) ---

Geom Title=USGS 3m DEM
Program Version=4.10

River Reach=WolfCreek       ,Main
Reach XY= 30
     1819859.516      604756.651     1820095.713      604645.516
     1820333.658      604338.136     1820297.216       603846.65
      1820946.74      603829.321       1821335.8      603125.983
     1822409.977      602560.231     1822570.658       601915.58
     1822833.038      601417.674      1822755.67      600962.494
     1822950.218      600274.775     1823304.337      599721.651
     1823439.126      599750.322     1823759.573      599258.856
     1824072.666      598278.251     1824927.331      597866.869
     1824883.335      597030.744     1825475.591      596682.921
     1825595.407      596488.935     1825659.676      596277.062
     1825545.208      596140.972      1825543.34      595865.461
     1825772.607      595427.827     1825699.684      595089.169
     1826194.678      594382.363     1826177.356      593543.541
     1826023.419       593342.62      1825519.79      593139.401
     1825905.373      592415.222     1825978.075      591986.476

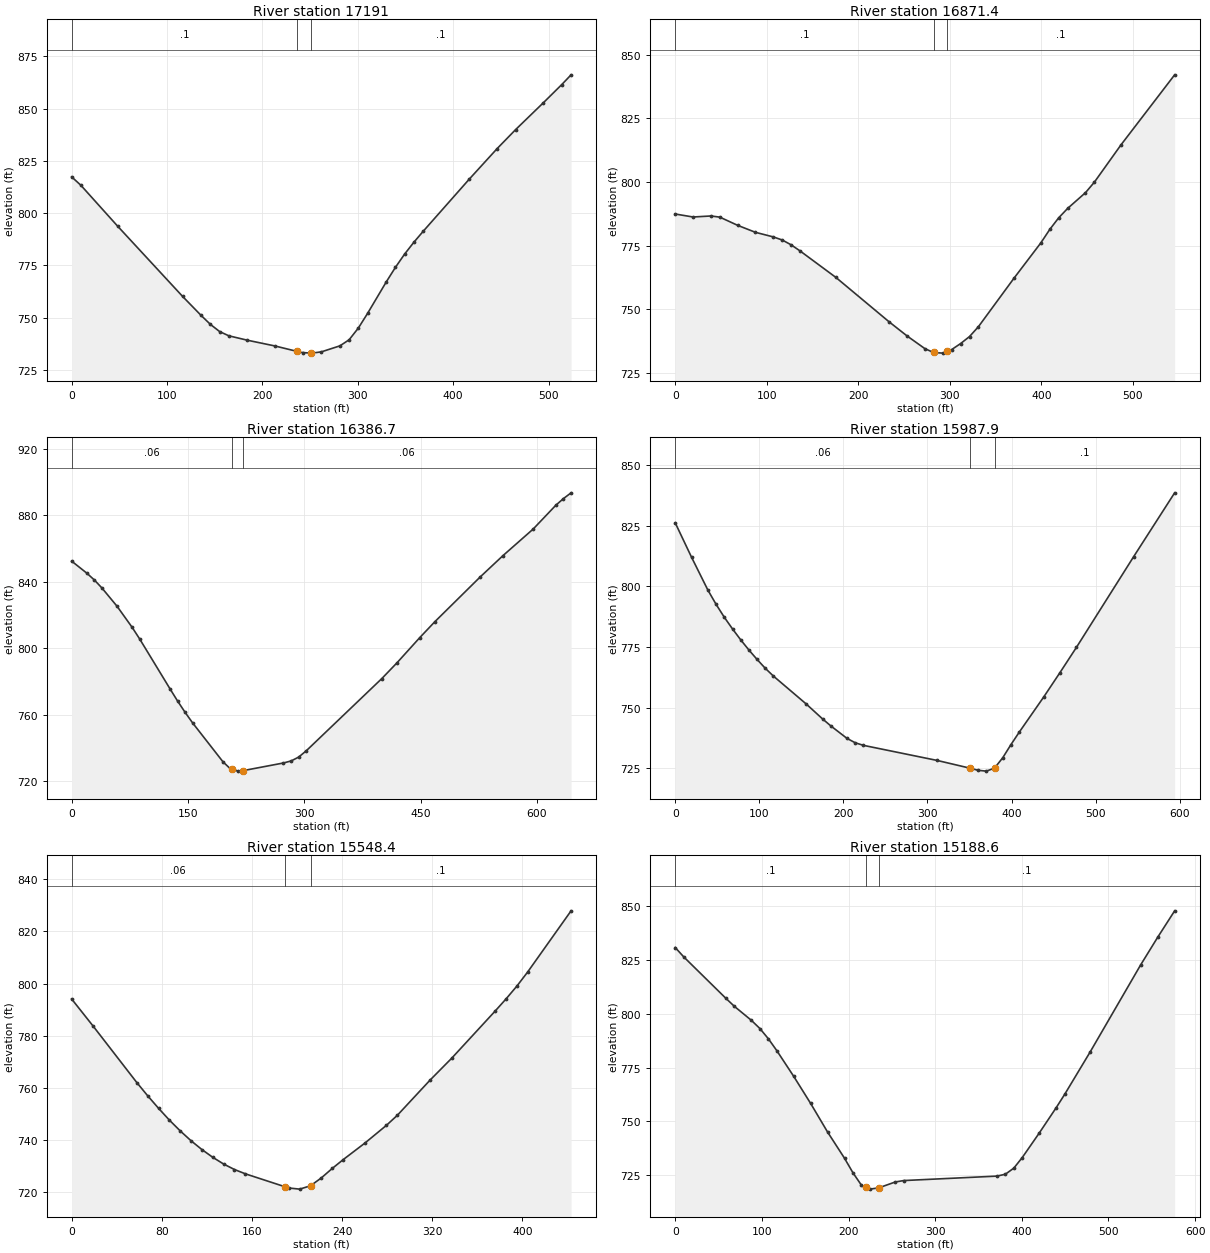
Type RM Length L Ch R = 1 ,17191   ,329.1,319.5,309.9
XS GIS Cut Line= 2
     1819978.444      604972.423     1819739.101      604506.681
#Sta/Elev= 30
       0  817.37     9.7  813.34    48.5  793.65   116.4  760.16   135.8  751.07
   145.5  746.81   155.2  743.37   164.8  741.35   184.2  739.25   213.3  736.48
   236.2  733.91   242.4  733.32   251.2  733.09   252.1  733.07   261.8  733.68
   281.2  736.54   290.9  739.45   300.6  745.08   310.3  752.11   329.7  767.02
   339.4  774.06   349.1  780.45   358.8   786.1   368.5  791.31     417  816.35
   446.1   830.9   465.5  839.99   494.6  852.84   513.9  861.54   523.6  866.17
#Mann= 3 , 0 , 0
       0      .1       0   236.2    .045       0   251.2      .1       0
Bank Sta=236.2,251.2
XS Rating Curve= 0 ,0
Exp/Cntr=0.3,0.1

Type RM Length L Ch R = 1 ,16871.4 ,500.6,484.7,468.9
XS GIS Cut Line= 2
     1820358.369       604772.61     1819927.246      604438.265
#Sta/Elev= 30
       0  787.46    19.5  786.29      39  786.69    48.7  786.24    68.2  783.02
    87.7  780.27   107.2  778.47   116.9  777.26   126.6  775.38   136.4  772.97
   175.4  762.61   233.8  745.11   253.3   739.6   272.8  734.61   282.2  733.11
   292.3  732.86   297.2  733.56     302  734.25   311.8  736.62   321.5  739.36
   331.2  743.22   370.2  762.32   399.4  776.12   409.2  781.42   418.9  785.96
   428.7  789.66   448.2  795.84   457.9  799.96   487.1  814.66   545.6  842.09
#Mann= 3 , 0 , 0
       0      .1       0   282.2    .045       0   297.2      .1       0
Bank Sta=282.2,297.2
XS Rating Curve= 0 ,0
Exp/Cntr=0.3,0.1

Type RM Length L Ch R = 1 ,16386.7 ,379.6,398.5,417.5
XS GIS Cut Line= 2
     1820528.867      604178.332     1819885.186      604201.404
#Sta/Elev= 30
       0  852.51    19.5  845.28    29.3  841.14      39  836.36    58.6   825.3
    78.1  812.57    87.8  805.58   126.9  775.56   136.6  768.27   146.4  761.38
   156.1  755.02   195.2  731.63   204.9  727.35   206.5  727.13   214.7  726.03
   221.5  726.36   273.2  730.94     283  732.15   292.8  734.49   302.5  738.24
   400.1  781.81   419.6  791.27   448.9   806.4   468.4  816.01     527  843.02
   556.3  855.83   595.3  871.85   624.6  886.24   634.3  890.17   644.1  893.63
#Mann= 3 , 0 , 0
       0     .06       0   206.5     .04       0   221.5     .06       0
Bank Sta=206.5,221.5
XS Rating Curve= 0 ,0
Exp/Cntr=0.3,0.1

Type RM Length L Ch R = 1 ,15987.9 ,423.4,439.3,455.2
XS GIS Cut Line= 2
      1820570.57      604088.969     1820157.386      603662.372
#Sta/Elev= 30
       0  826.22    19.5  811.97    38.9  798.43    48.7  792.53    58.4  787.24
    68.2  782.41    77.9  777.93    87.6  773.75    97.4  769.83   107.1  766.19
   116.8  762.97   155.8  751.46   175.2  745.31     185  742.43   204.4  737.24
   214.2  735.44   223.9  734.39   311.6  728.16   350.5  724.98   360.2   724.1
     370  723.76   379.7     725   389.4  729.24   399.2  734.68   408.9  739.74
   438.1   754.3   457.6  764.45   477.1  774.82   545.2  812.28   593.9  838.59
#Mann= 3 , 0 , 0
       0     .06       0   350.5    .045       0   379.7      .1       0
Bank Sta=350.5,379.7
XS Rating Curve= 0 ,0
Exp/Cntr=0.3,0.1

Type RM Length L Ch R = 1 ,15548.4 ,381.7,359.6,337.5
XS GIS Cut Line= 2
     1820757.698      604041.999     1820726.523      603599.845
#Sta/Elev= 30
       0  794.11    19.3  783.59    57.8  762.11    67.4  757.06    77.1  752.24
    86.7  747.72    96.4  743.55     106  739.78   115.6  736.42   125.3  733.43
   134.9  730.87   144.5  728.77   154.2  727.12   189.3  722.17   192.7  721.69
   202.4  721.26     212  722.55   221.6  725.57   231.3   729.2   240.9  732.54
   260.2  738.89   279.4  745.72   289.1  749.58     318     763   337.3  771.43
   375.8  789.47   385.4  794.09   395.1  799.04   404.7  804.46   443.2  827.88
#Mann= 3 , 0 , 0
       0     .06       0   189.3    .045       0     212      .1       0
Bank Sta=189.3,212
XS Rating Curve= 0 ,0
Exp/Cntr=0.3,0.1

Type RM Length L Ch R = 1 ,15188.6 ,358.8,360,361.1
XS GIS Cut Line= 2
     1821243.637      603831.688     1820745.205      603542.238
#Sta/Elev= 30
       0   830.9     9.8  826.55    58.6  807.19    68.4  803.46    87.9  796.99
    97.7  793.18   107.5  788.41   117.2   782.9   136.8  770.88   156.3  758.29
   175.8     745   195.4  732.76   205.2  725.94   214.9  720.23   219.9  719.29
   224.7  718.38   234.9  718.97     254  721.71   263.8  722.37   371.2  724.44
     381  725.31   390.8  728.16   400.5  733.08   420.1  744.48   439.6  756.25
   449.4  762.46   478.7  782.13   537.3  822.89   556.8  835.65   576.4  847.98
#Mann= 3 , 0 , 0
       0      .1       0   219.9    .045       0   234.9      .1       0
Bank Sta=219.9,234.9
XS Rating Curve= 0 ,0
Exp/Cntr=0.3,0.1

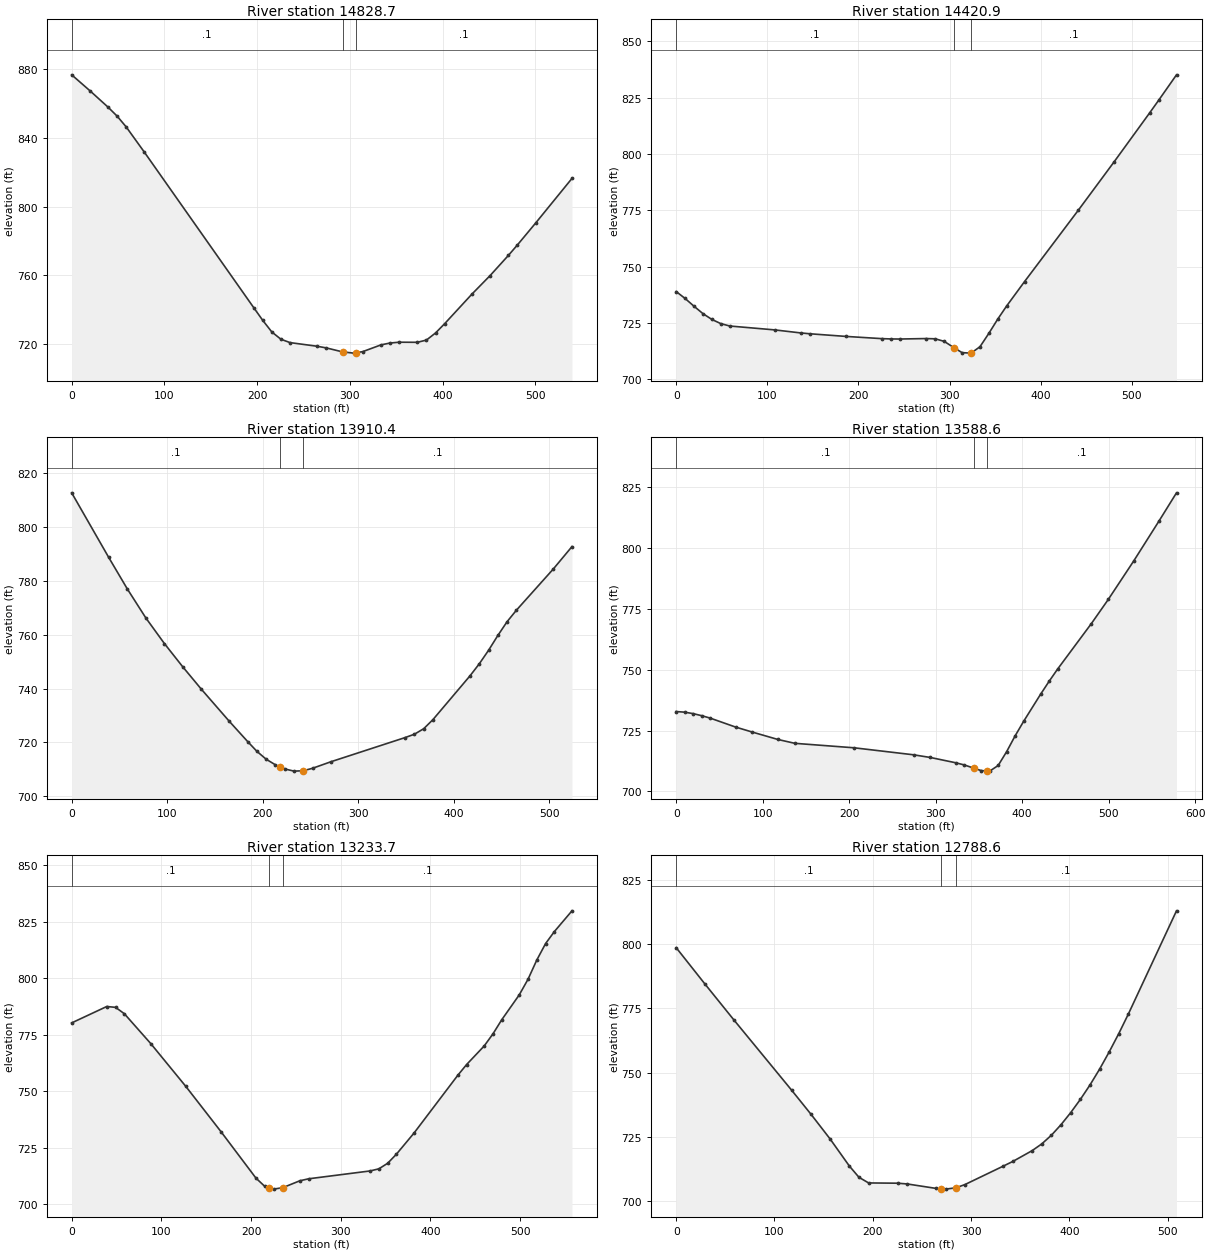
Type RM Length L Ch R = 1 ,14828.7 ,397.1,407.5,417.9
XS GIS Cut Line= 2
     1821437.178      603549.222     1820984.485      603255.887
#Sta/Elev= 30
       0  876.73    19.6   867.5    39.2  857.91      49  852.68    58.8  846.38
    78.5  831.59   196.2   741.2     206  733.75   215.8  726.98   225.6  722.76
   235.4   720.8   264.8  718.66   274.6   717.7     292   715.4     304  714.67
     307  714.94   313.8  715.54   333.5  719.48   343.3  720.56   353.1  721.03
   372.7  720.97   382.5  722.28   392.3  726.41   402.1   731.8   431.5  749.02
   451.2  759.87   470.8  771.55   480.6  777.69   500.2  790.41   539.4  816.42
#Mann= 3 , 0 , 0
       0      .1       0     292    .045       0     307      .1       0
Bank Sta=292,307
XS Rating Curve= 0 ,0
Exp/Cntr=0.3,0.1

Type RM Length L Ch R = 1 ,14420.9 ,511.7,510.4,509.1
XS GIS Cut Line= 2
     1821583.659      603345.284     1821305.334      602871.921
#Sta/Elev= 30
       0  738.93     9.8  735.86    19.6   732.4    29.4  729.12    39.2  726.55
      49  724.69    58.8  723.64   107.9  721.92   137.3  720.54   147.1  720.18
   186.3  719.02   225.5  718.04   235.3   717.9   245.1  717.86   274.6  718.07
   284.4  717.95   294.2  716.81   304.9  714.01   313.8  711.81   323.6   711.6
   333.4  714.43   343.2  720.41     353  726.76   362.8   732.6   382.4   743.4
   441.3  775.03   480.5  796.46   519.7   818.3   529.5  823.85   549.1  835.16
#Mann= 3 , 0 , 0
       0      .1       0   304.9    .045       0   323.6      .1       0
Bank Sta=304.9,323.6
XS Rating Curve= 0 ,0
Exp/Cntr=0.3,0.1

Type RM Length L Ch R = 1 ,13910.4 ,317.8,321.7,325.5
XS GIS Cut Line= 2
     1822012.067      603050.158     1821721.198      602614.825
#Sta/Elev= 30
       0  812.77    38.8  788.74    58.2  777.06    77.6  766.28      97  756.76
   116.4  748.03   135.7  739.78   164.8  727.91   184.2  720.31   193.9  716.67
   203.6  713.74   213.3  711.66   217.8  710.95     223  710.14   232.7  709.33
   242.4  709.47   252.1  710.39   271.5  712.84     349  721.81   358.7  723.05
   368.4  725.09   378.1  728.48   416.9  744.76   426.6  749.23   436.3  754.24
     446  759.75   455.7  764.88   465.4  769.13   504.2  784.52   523.6  792.79
#Mann= 3 , 0 , 0
       0      .1       0   217.8    .045       0   242.4      .1       0
Bank Sta=217.8,242.4
XS Rating Curve= 0 ,0
Exp/Cntr=0.3,0.1

Type RM Length L Ch R = 1 ,13588.6 ,373.6,354.7,335.9
XS GIS Cut Line= 3
     1822274.324        602993.6     1822038.409      602465.821
     1822038.266        602465.5
#Sta/Elev= 30
       0  732.79     9.8  732.54    19.6  731.94    29.4   731.1    39.2  730.11
    68.6  726.43    88.2  724.34   117.6  721.32   137.2  719.74   205.8   717.9
   274.4  715.03     294  713.92   323.4  711.74   333.2  710.85   344.7  709.47
   352.7  708.53   359.7  708.38   362.5  708.32   372.3  710.64   382.1  716.32
   391.9  722.81   401.7  728.75   421.3  739.87   431.1  745.16   440.9  750.18
   480.1  768.94   499.7  778.88   529.1  794.68   558.5  811.18   578.5  822.63
#Mann= 3 , 0 , 0
       0      .1       0   344.7    .045       0   359.7      .1       0
Bank Sta=344.7,359.7
XS Rating Curve= 0 ,0
Exp/Cntr=0.3,0.1

Type RM Length L Ch R = 1 ,13233.7 ,446.9,445,443.2
XS GIS Cut Line= 2
     1822640.192      602588.891     1822111.874      602410.093
#Sta/Elev= 30
       0  780.19    39.1  787.45    48.9  787.08    58.7  784.26    88.1  771.06
   127.2   752.1   166.4  732.06   205.5  711.44   215.3   707.8   220.3  707.18
   225.1  706.58   235.3  707.22   254.4  710.28   264.2  711.16   332.7  714.63
   342.5  715.57   352.3  718.03     362  722.03   381.6  731.37   430.6  757.05
   440.3  761.74   459.9  769.97   469.7  775.33   479.5  781.59     499   792.6
   508.8  799.53   518.6  808.05   528.4  815.35   538.2  820.65   557.8  829.82
#Mann= 3 , 0 , 0
       0      .1       0   220.3    .045       0   235.3      .1       0
Bank Sta=220.3,235.3
XS Rating Curve= 0 ,0
Exp/Cntr=0.3,0.1

Type RM Length L Ch R = 1 ,12788.6 ,395,400,404.9
XS GIS Cut Line= 2
     1822792.726      602150.556     1822298.738      602027.468
#Sta/Elev= 30
       0  798.69    29.4  784.47    58.7  770.55   117.5  743.16   137.1  733.83
   156.6  724.18   176.2  713.63     186  709.23   195.8  707.04   225.2  706.94
     235  706.65   264.3  704.92   269.6  704.76   274.1  704.63   284.6  705.14
   293.7  706.39   332.9  713.61   342.7  715.45   362.2  719.62     372  722.25
   381.8  725.63   391.6  729.74   401.4  734.41   411.2  739.55     421  745.17
   430.8  751.34   440.6  758.08   450.4  765.25   460.1  772.83   509.1  813.05
#Mann= 3 , 0 , 0
       0      .1       0   269.6    .045       0   284.6      .1       0
Bank Sta=269.6,284.6
XS Rating Curve= 0 ,0
Exp/Cntr=0.3,0.1

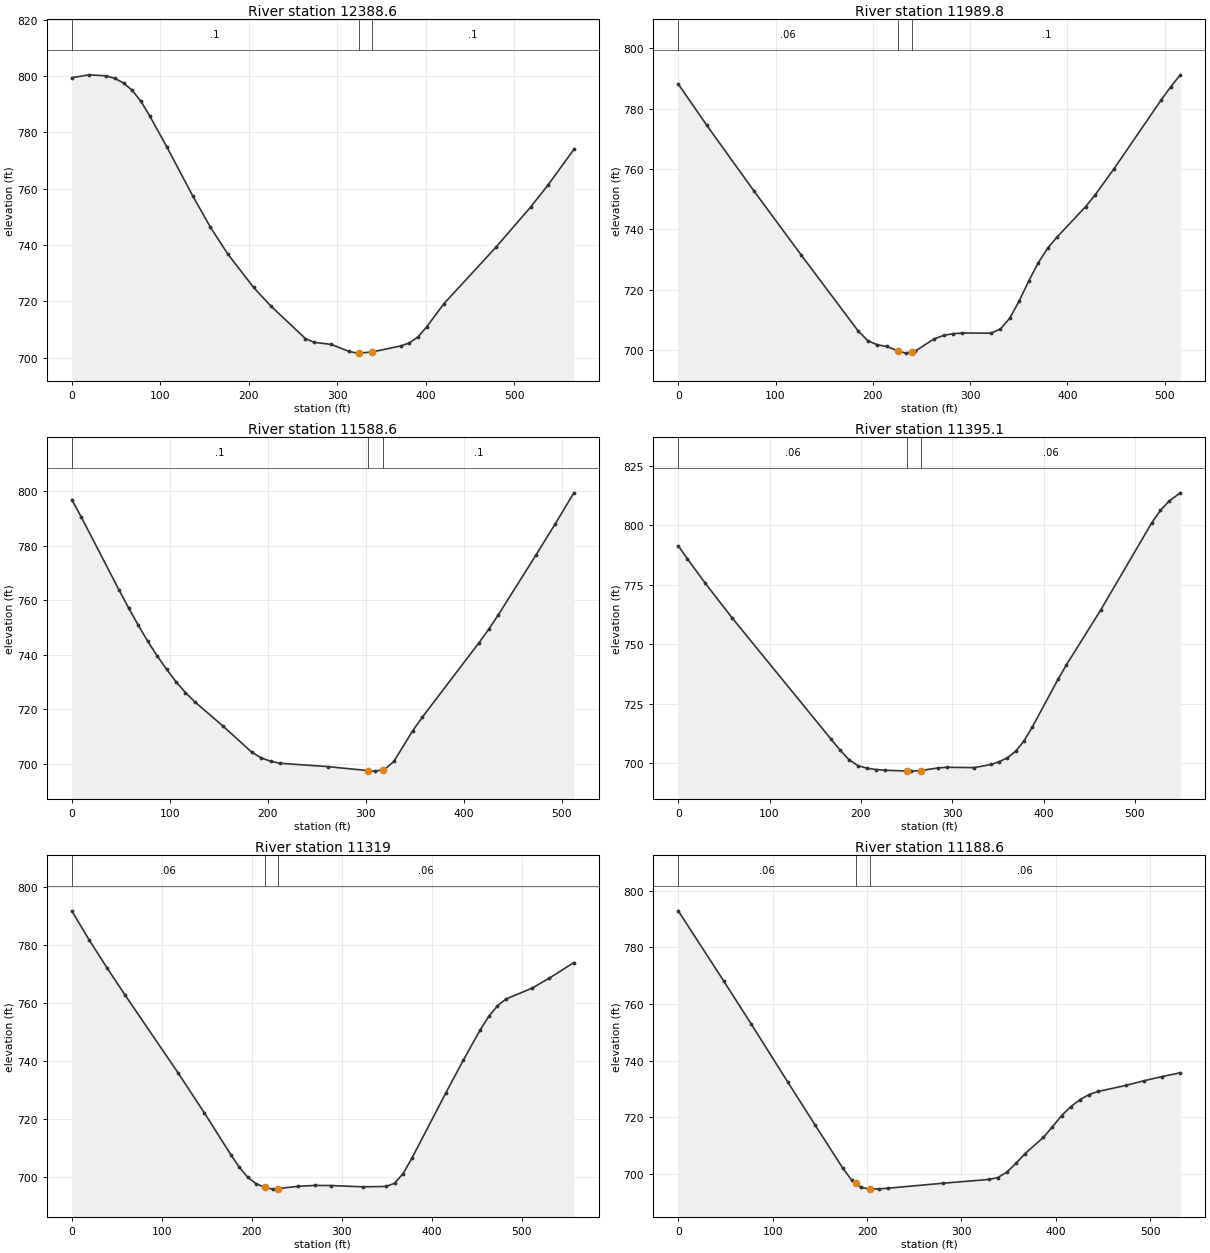
Type RM Length L Ch R = 1 ,12388.6 ,413.6,398.7,383.9
XS GIS Cut Line= 2
      1822977.83      601869.471     1822470.546      601615.829
#Sta/Elev= 30
       0  799.42    19.6  800.45    39.1  800.08    48.9  799.15    58.7   797.5
    68.4   794.9    78.2  791.01      88  785.91   107.6  774.74   136.9  757.33
   156.5  746.43     176  736.97   205.4  724.98   224.9  718.39     264  706.81
   273.8  705.51   293.4  704.73   312.9  702.29   322.7  701.66   324.1  701.67
   339.1  702.06   371.6  704.22   381.4  705.27   391.2  707.45   400.9  710.97
   420.5  719.25   479.2  739.25   518.3   753.5   537.8  761.25   567.2  773.96
#Mann= 3 , 0 , 0
       0      .1       0   324.1    .045       0   339.1      .1       0
Bank Sta=324.1,339.1
XS Rating Curve= 0 ,0
Exp/Cntr=0.3,0.1

Type RM Length L Ch R = 1 ,11989.8 ,394.3,401.2,408
XS GIS Cut Line= 2
      1823061.19      601315.699     1822554.461      601413.813
#Sta/Elev= 30
       0  788.14    29.2   774.5    77.9  752.64   126.6  731.35     185  706.24
   194.8  703.04   204.5  701.69   214.2  701.12   225.5  699.73   233.7  698.91
   240.5  699.35   243.5  699.55   262.9  703.61   272.7  704.77   282.4  705.36
   292.2  705.58   321.4  705.53   331.1  706.87   340.8   710.5   350.6  716.29
   360.3  722.85   370.1  728.86   379.8  733.72   389.5  737.42   418.8  747.48
   428.5  751.35     448  760.06   496.7  782.96   506.4  787.27   516.1  791.17
#Mann= 3 , 0 , 0
       0     .06       0   225.5    .045       0   240.5      .1       0
Bank Sta=225.5,240.5
XS Rating Curve= 0 ,0
Exp/Cntr=0.3,0.1

Type RM Length L Ch R = 1 ,11588.6 ,186.5,193.6,200.6
XS GIS Cut Line= 2
     1823063.864      601010.839     1822554.731      600953.914
#Sta/Elev= 30
       0   796.9     9.7  790.49    48.3   763.7      58   757.2    67.7  750.97
    77.3   745.1      87  739.72    96.7  734.75   106.3  730.18     116  726.18
   125.7  722.74   154.7  713.77   183.7  704.32   193.3  702.23     203  701.01
   212.6  700.26     261  699.06   302.6  697.56   309.3  697.39   317.6  697.87
     319  697.95   328.6  700.92     348  712.26   357.6  717.11   415.6  744.48
   425.3  749.29     435  754.53   473.6  776.55     493  787.82   512.3  799.37
#Mann= 3 , 0 , 0
       0      .1       0   302.6    .045       0   317.6      .1       0
Bank Sta=302.6,317.6
XS Rating Curve= 0 ,0
Exp/Cntr=0.3,0.1

Type RM Length L Ch R = 1 ,11395.1 ,76,76,76.1
XS GIS Cut Line= 6
     1823065.403      600835.362     1822869.355       600819.52
      1822744.19      600763.621     1822717.153      600728.193
     1822548.869      600736.254     1822545.853      600736.399
#Sta/Elev= 30
       0  791.43     9.8  786.02    29.5  775.71      59  761.08   167.2  710.15
     177   705.6   186.8  701.53   196.7  698.98   206.5  697.91   216.3  697.32
   226.1  697.04     251   696.7   255.4  696.65     266  696.91   284.8  698.02
   294.6  698.26     324  698.11   342.7  699.47   351.6  700.63   360.5  702.28
   369.4     705   378.3  709.18   387.7  715.16   415.8  735.19   425.1  741.34
   462.6  764.37   518.7  801.16   528.1  806.28   537.4  810.15   549.8  813.65
#Mann= 3 , 0 , 0
       0     .06       0     251     .04       0     266     .06       0
Bank Sta=251,266
XS Rating Curve= 0 ,0
Exp/Cntr=0.3,0.1

Type RM Length L Ch R = 1 ,11319   ,138.4,130.3,122.1
XS GIS Cut Line= 6
      1823066.06       600760.45     1822889.945      600746.218
     1822788.123      600700.745     1822751.251       600652.43
     1822551.508      600661.999     1822542.833      600662.414
#Sta/Elev= 30
       0  791.89    19.6  781.71    39.3  772.13    58.9  762.97   117.8  736.08
   147.2  722.18   176.7   707.7     186   703.4   195.3  699.98   204.6  697.74
   214.4  696.41   223.2  695.83   229.4     696     251   696.8   269.6   697.1
   288.2  697.07   322.9  696.63     349  696.76   358.5  697.85     368  701.21
   377.6  706.42   415.6  729.14   434.7  740.27   453.7  750.85   463.2  755.49
   472.8  759.12   482.3  761.46   510.9  765.16   529.9  768.56   557.6  774.03
#Mann= 3 , 0 , 0
       0     .06       0   214.4     .04       0   229.4     .06       0
Bank Sta=214.4,229.4
XS Rating Curve= 0 ,0
Exp/Cntr=0.3,0.1

Type RM Length L Ch R = 1 ,11188.6 ,429.2,446,462.8
XS GIS Cut Line= 2
     1823070.455      600615.276     1822539.601      600583.217
#Sta/Elev= 30
       0  792.91    48.4     768    77.4  752.87     116  732.43     145  717.23
     174  702.16   183.7  697.74   187.8  696.67   193.4   695.2   202.8  694.61
   203.1  694.59   212.7  694.68   222.4  694.92   280.4  696.68   328.8     698
   338.4  698.66   348.1   700.6   357.8  703.74   367.4  707.13   386.8  712.89
   396.4  716.59   406.1  720.58   415.8  723.74   425.5  726.18   435.1     728
   444.8   729.1   473.8  731.21   493.1  732.86   512.5  734.36   531.8  735.71
#Mann= 3 , 0 , 0
       0     .06       0   187.8     .04       0   202.8     .06       0
Bank Sta=187.8,202.8
XS Rating Curve= 0 ,0
Exp/Cntr=0.3,0.1

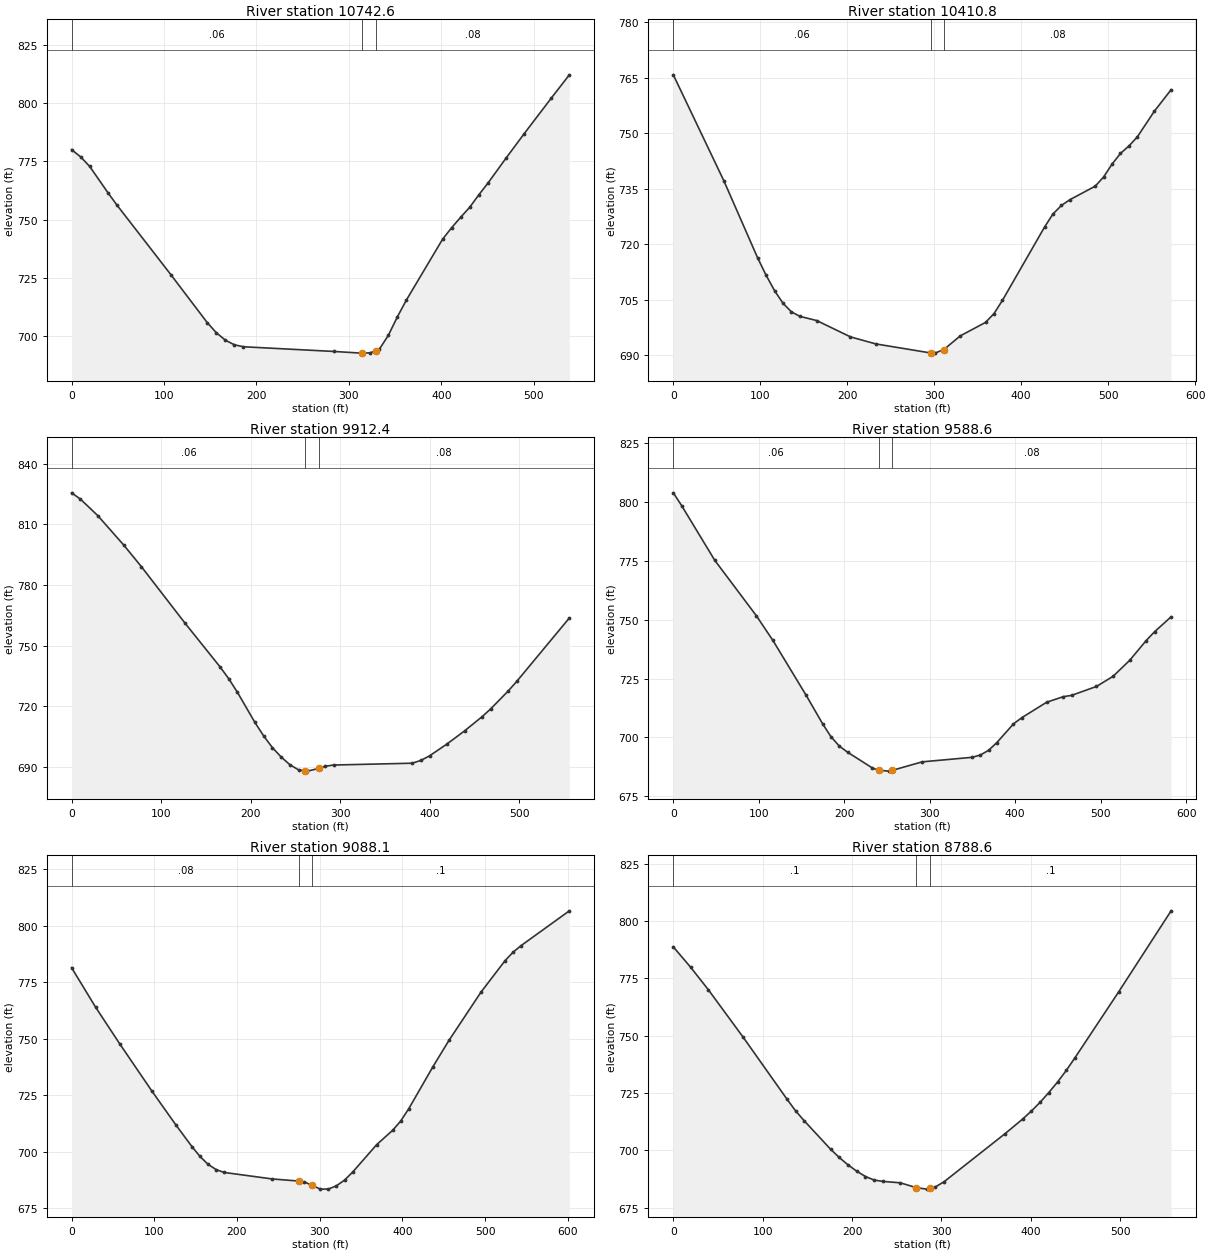
Type RM Length L Ch R = 1 ,10742.6 ,342.6,331.5,320.5
XS GIS Cut Line= 2
     1823237.188      600423.171     1822861.936      600036.996
#Sta/Elev= 30
       0   780.1     9.8  776.99    19.6  772.87    39.2  761.63      49  756.26
   107.7   726.1   146.8  705.58   156.6  701.23   166.4  698.02   176.2  696.02
     186  695.18   283.9  693.16   313.3  692.44     314  692.45   323.1  692.57
     329  693.49   332.9   694.1   342.7   700.1   352.4  708.02   362.2   715.3
   401.4  741.53   411.2  746.49     421  750.99   430.8  755.32   440.6  760.65
   450.4  765.65   469.9  776.38   489.5  786.89   518.9  802.26   538.5  812.32
#Mann= 3 , 0 , 0
       0     .06       0     314    .045       0     329     .08       0
Bank Sta=314,329
XS Rating Curve= 0 ,0
Exp/Cntr=0.3,0.1

Type RM Length L Ch R = 1 ,10410.8 ,490.3,497.9,504.3
XS GIS Cut Line= 2
     1823539.113      600067.877     1822994.974      599890.195
#Sta/Elev= 30
       0  765.79    58.2  737.13      97  716.32   106.7  711.64   116.4  707.49
   126.1  704.08   135.8  701.76   145.5  700.54   164.9   699.4   203.7  694.99
   232.8  693.09   296.1  690.64   300.8   690.6   311.1  691.57   329.9  695.25
     359   698.9   368.7  701.27   378.4  704.83   426.9  724.67   436.6  728.21
   446.3   730.5     456  732.05   485.1   735.7   494.8  738.19   504.5  741.66
   514.2  744.56   523.9  746.57   533.6  749.03     553  755.91   572.4  761.77
#Mann= 3 , 0 , 0
       0     .06       0   296.1    .045       0   311.1     .08       0
Bank Sta=296.1,311.1
XS Rating Curve= 0 ,0
Exp/Cntr=0.3,0.1

Type RM Length L Ch R = 1 ,9912.4  ,325,323.6,321
XS GIS Cut Line= 2
     1823676.361      599845.859     1823233.963      599508.753
#Sta/Elev= 30
       0  825.58     9.8  822.52    29.3   814.3    58.6  799.58    78.1     789
   126.8  761.07   165.9  739.45   175.6   733.6   185.4  726.82   204.9  711.92
   214.7  705.24   224.4  699.48   234.2  694.86     244     691   253.7  688.47
   261.3  687.99   263.5  687.85   276.3   689.2     283  690.21   292.7  690.87
   380.6  691.77   390.3  693.15   400.1  695.45   419.6  701.31   439.1  707.76
   458.6  714.75   468.4   718.7   487.9  727.52   497.6  732.35   556.2  763.65
#Mann= 3 , 0 , 0
       0     .06       0   261.3    .045       0   276.3     .08       0
Bank Sta=261.3,276.3
XS Rating Curve= 0 ,0
Exp/Cntr=0.3,0.1

Type RM Length L Ch R = 1 ,9588.6  ,508.6,500.5,493.5
XS GIS Cut Line= 2
     1823816.973      599572.479     1823356.819      599215.413
#Sta/Elev= 30
       0  803.87     9.7  798.46    48.5  775.22    97.1  751.71   116.5  741.21
   155.3  717.98   174.7  705.79   184.4  700.34   194.2  696.34   203.8  693.76
     233     687   240.6  686.06   252.4   685.7   255.6  685.97   291.2  689.64
   349.5  691.56   359.2  692.54   368.9  694.54   378.6  697.84     398  705.77
   407.7  708.39   436.8  714.95   456.2  717.31     466  717.87   495.1  721.66
   514.5  725.95   533.9  732.73   553.3  741.16     563  744.87   582.4  751.22
#Mann= 3 , 0 , 0
       0     .06       0   240.6    .045       0   255.6     .08       0
Bank Sta=240.6,255.6
XS Rating Curve= 0 ,0
Exp/Cntr=0.3,0.1

Type RM Length L Ch R = 1 ,9088.1  ,294.1,299.4,304.8
XS GIS Cut Line= 2
     1824096.308      599063.671      1823509.57      598929.712
#Sta/Elev= 30
       0  781.41    29.1  763.89    58.2  747.71    97.1   726.8   126.2  711.76
   145.6  702.17   155.3  697.83     165  694.36   174.7  692.04   184.4  690.77
   242.7  687.88   275.3  686.93   281.5  686.58   290.3  685.11   300.9  683.38
   310.6  683.42   320.3  684.87     330  687.36   339.8   690.9   368.9  703.08
   388.3  709.46     398  713.57   407.7     719   436.8  737.51   456.2  749.19
   495.1  770.64   524.2  784.56   533.9  788.31   543.6   791.2   601.8  806.56
#Mann= 3 , 0 , 0
       0     .08       0   275.3    .045       0   290.3      .1       0
Bank Sta=275.3,290.3
XS Rating Curve= 0 ,0
Exp/Cntr=0.3,0.1

Type RM Length L Ch R = 1 ,8788.6  ,262.1,257.1,252.1
XS GIS Cut Line= 2
     1824180.883      598854.876     1823682.746       598605.81
#Sta/Elev= 30
       0  788.71    19.5  779.76    39.1  770.06    78.2  749.28     127  722.39
   136.8   717.2   146.6   712.8   175.9  700.49   185.6  696.87   195.4  693.67
   205.2  690.88     215  688.56   224.7  687.02   234.5  686.43     254  685.81
     272  683.68   283.4  683.06     287  683.41   293.1     684   302.9  686.28
   371.3  707.29   390.8  713.61   400.6   717.1   410.4  720.95   420.1  725.18
   429.9  729.77   439.7  734.86   449.5  740.43   498.3  769.12   556.9  804.42
#Mann= 3 , 0 , 0
       0      .1       0     272    .045       0     287      .1       0
Bank Sta=272,287
XS Rating Curve= 0 ,0
Exp/Cntr=0.3,0.1

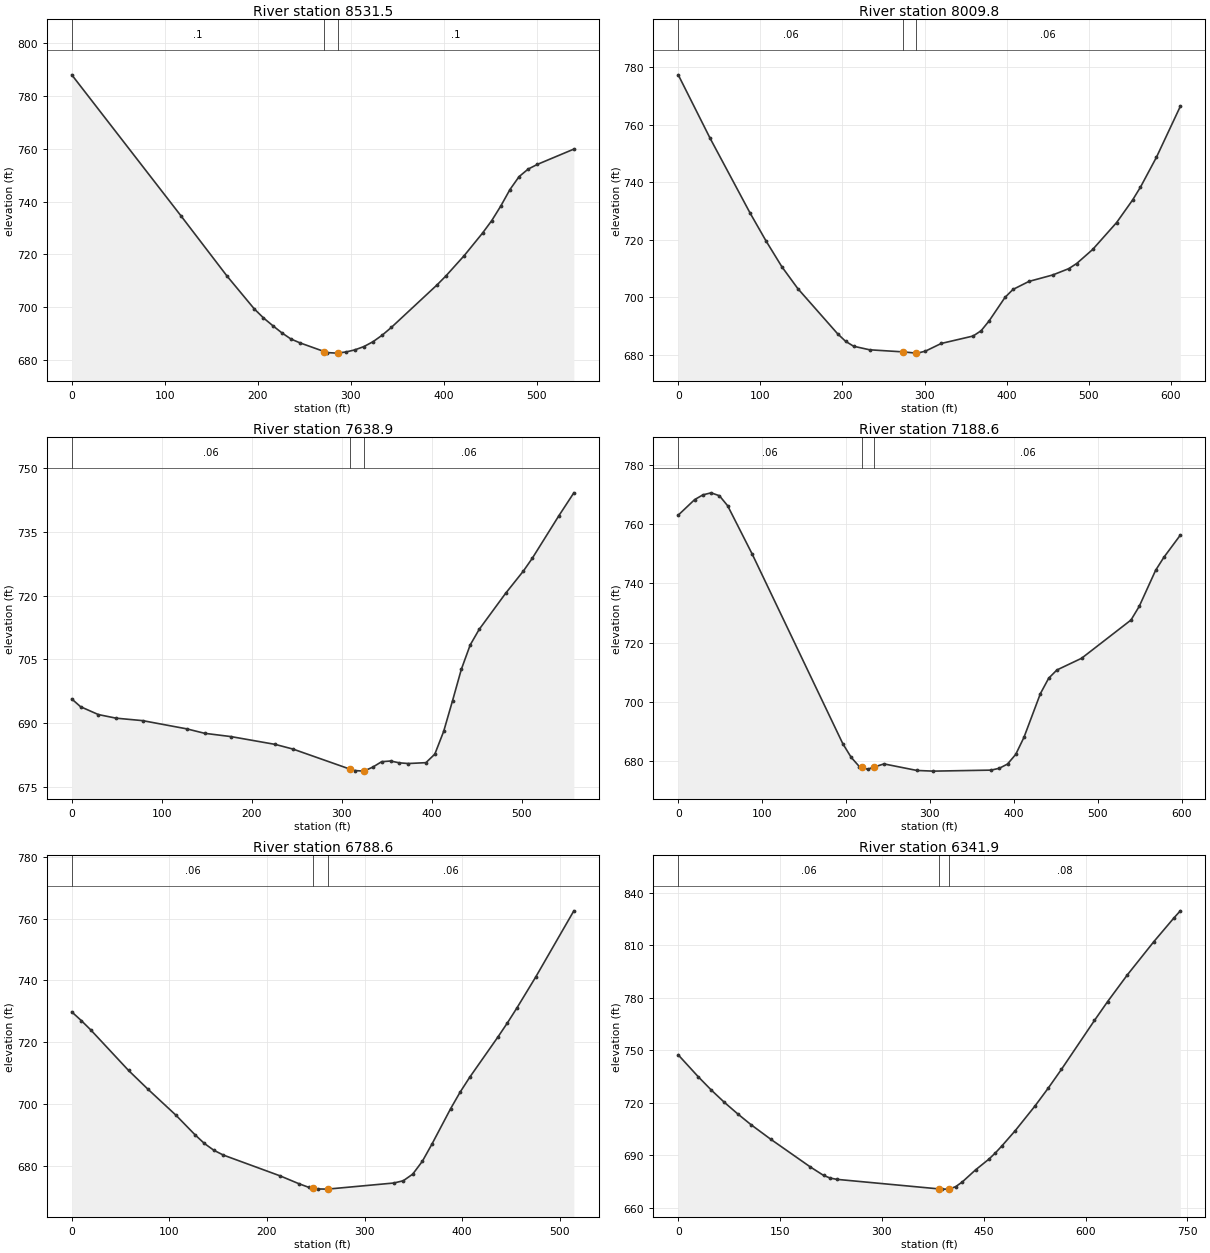
Type RM Length L Ch R = 1 ,8531.5  ,502.3,521.7,541.1
XS GIS Cut Line= 2
      1824300.32      598560.017     1823775.955      598431.474
#Sta/Elev= 30
       0  788.03   117.8   734.4   166.9  711.76   196.3  699.27   206.1  695.89
     216  692.98   225.8  690.24   235.6  687.89   245.4  686.41   271.6   683.1
   274.8  682.73   284.7  682.52   286.6   682.6   294.5  682.93   304.3  683.74
   314.1     685   323.9  686.84   333.8  689.32   343.6  692.25   392.6  708.32
   402.5  711.85   422.1  719.53   441.7  728.03   451.6  732.76   461.4  738.33
   471.2  744.54     481  749.44   490.8   752.3   500.6  754.06   539.9  759.87
#Mann= 3 , 0 , 0
       0      .1       0   271.6    .045       0   286.6      .1       0
Bank Sta=271.6,286.6
XS Rating Curve= 0 ,0
Exp/Cntr=0.3,0.1

Type RM Length L Ch R = 1 ,8009.8  ,372.5,370.6,368.6
XS GIS Cut Line= 2
     1824453.853      598380.128     1824176.616      597835.058
#Sta/Elev= 30
       0  777.24    38.8  755.24    87.4  729.35   106.8  719.68   126.2  710.67
   145.6   703.1   194.1  687.42   203.8  684.81   213.6  683.09     233  681.86
   274.3  681.12   289.3  680.72   291.2   680.7   300.9  681.37   320.3  684.05
   359.2  686.64   368.9  688.47   378.6  691.87     398  700.04   407.7  702.79
   427.1  705.57   456.2  707.82   475.6     710   485.3  711.79   504.8  716.67
   533.9  725.99   553.3  733.78     563   738.3   582.4  748.63   611.5   766.3
#Mann= 3 , 0 , 0
       0     .06       0   274.3    .045       0   289.3     .06       0
Bank Sta=274.3,289.3
XS Rating Curve= 0 ,0
Exp/Cntr=0.3,0.1

Type RM Length L Ch R = 1 ,7638.9  ,472.4,450.4,428.4
XS GIS Cut Line= 3
     1824831.428      598254.264     1824541.278      597785.747
      1824537.66      597779.904
#Sta/Elev= 30
       0   695.7     9.8  693.87    29.5  692.03    49.2  691.18    78.7   690.6
   127.9  688.66   147.6  687.62   177.1  686.84   226.3     685     246   683.9
   309.6  679.16   314.9  678.85   324.6  678.72   334.6  679.67   344.4  680.94
   354.3   681.1   364.1  680.67     374  680.51   393.6  680.71   403.5  682.72
   413.3  688.06   423.2   695.3     433   702.7   442.8   708.4   452.7  712.04
   482.2  720.56   501.9  725.79   511.7  728.76   541.2  738.75     558  744.19
#Mann= 3 , 0 , 0
       0     .06       0   309.6    .045       0   324.6     .06       0
Bank Sta=309.6,324.6
XS Rating Curve= 0 ,0
Exp/Cntr=0.3,0.1

Type RM Length L Ch R = 1 ,7188.6  ,397.5,399.5,401.5
XS GIS Cut Line= 2
     1825178.387      597724.186     1824580.367      597699.235
#Sta/Elev= 30
       0  763.07    19.6  768.33    29.4  769.92    39.2  770.61    49.1  769.62
    58.9  766.25    88.3  749.84   196.2  685.85   206.1  681.28   215.9  678.13
   218.8  677.87   225.7  677.24   233.8  678.01   245.3  679.04   284.6  676.82
   304.2   676.6   372.9  676.94   382.7  677.56   392.5  678.99   402.3  682.25
   412.1     688   431.7  702.78   441.6  707.99   451.4  710.77   480.8  714.72
   539.7  727.64   549.5  732.25   569.1  744.46   578.9  748.83   598.5  756.32
#Mann= 3 , 0 , 0
       0     .06       0   218.8    .045       0   233.8     .06       0
Bank Sta=218.8,233.8
XS Rating Curve= 0 ,0
Exp/Cntr=0.3,0.1

Type RM Length L Ch R = 1 ,6788.6  ,437,447.1,457.2
XS GIS Cut Line= 2
      1825129.54      597348.109     1824616.826      597305.694
#Sta/Elev= 30
       0   729.8     9.7  727.01    19.4  723.99    58.2  710.84    77.7  704.88
   106.8  696.34   126.2  690.05   135.9   687.2   145.6     685   155.3  683.45
   213.6   676.7     233  674.14   242.7  673.02   247.4  672.76   252.4  672.48
   262.1  672.42   262.4  672.43     330   674.4   339.7  675.13   349.4  677.28
   359.2  681.41   368.9  686.89   388.3  698.51     398  703.84   407.7   708.6
   436.8  721.72   446.5  726.28   456.2   731.1   475.6  741.19   514.5  762.52
#Mann= 3 , 0 , 0
       0     .06       0   247.4    .045       0   262.4     .06       0
Bank Sta=247.4,262.4
XS Rating Curve= 0 ,0
Exp/Cntr=0.3,0.1

Type RM Length L Ch R = 1 ,6341.9  ,318.3,326.7,335.2
XS GIS Cut Line= 2
      1825321.07      597164.787     1824703.819      596757.447
#Sta/Elev= 30
       0  747.48    29.2   735.1    48.6  727.42    68.1  720.31    87.6  713.78
     107  707.66   136.2   699.3   194.6  683.45   214.1  678.62   223.8  677.11
   233.5  676.38   384.1  670.91   389.2  670.79   399.1  670.83   408.7  672.21
   418.4   674.9   437.9  681.78   457.4  687.86   467.1  691.47   476.8  695.51
   496.3  704.16   525.5   718.3   544.9  728.45   564.4  739.19     613  767.12
   632.5  777.96   661.7  793.28   700.6   812.2   729.8  825.57   739.5  829.76
#Mann= 3 , 0 , 0
       0     .06       0   384.1    .045       0   399.1     .08       0
Bank Sta=384.1,399.1
XS Rating Curve= 0 ,0
Exp/Cntr=0.3,0.1

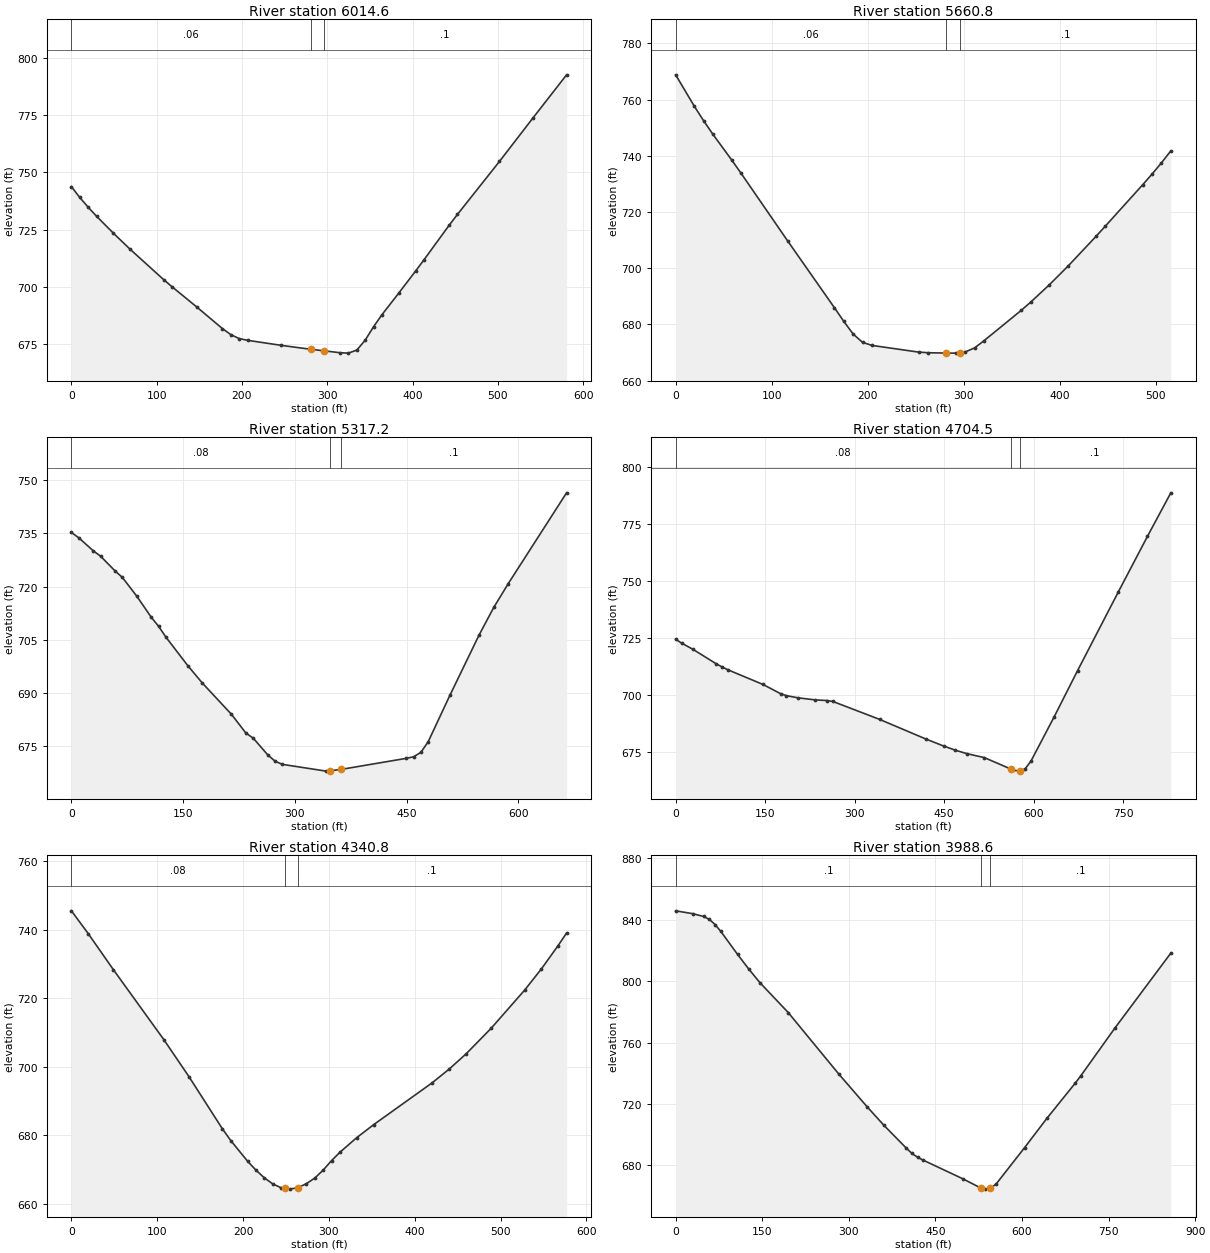
Type RM Length L Ch R = 1 ,6014.6  ,360.7,353.6,346.5
XS GIS Cut Line= 2
     1825454.726       597036.86      1825113.44      596567.166
#Sta/Elev= 30
       0  743.78     9.8  739.04    19.7  734.77    29.5  730.83    49.2  723.43
    68.9  716.37   108.2   703.1   118.1  699.96   147.6  690.95   177.1  681.68
     187  679.03   196.8  677.32   206.6  676.56     246  674.36   280.6  672.64
   295.6     672   314.9  671.14   324.7  670.96   334.6  672.28   344.4   676.6
   354.3  682.52   364.1  687.76   383.8  697.21   403.5  706.83   413.3  711.73
   442.8  726.84   452.7  731.67   501.9  754.81   541.2  773.84   580.6   792.7
#Mann= 3 , 0 , 0
       0     .06       0   280.6    .045       0   295.6      .1       0
Bank Sta=280.6,295.6
XS Rating Curve= 0 ,0
Exp/Cntr=0.3,0.1

Type RM Length L Ch R = 1 ,5660.8  ,363.9,343.6,323.3
XS GIS Cut Line= 2
     1825753.587      596750.807     1825334.495       596450.49
#Sta/Elev= 30
       0  768.81    19.5   757.6    29.2  752.43    38.9   747.6    58.4  738.49
    68.1  733.79   116.7  709.68   165.4  685.91   175.1  681.08   184.8  676.59
   194.6  673.63   204.3  672.54   252.9  670.16   262.7  669.93   281.2  669.81
   291.8  669.79   296.2  669.98   301.6  670.22   311.3  671.66     321  674.18
   359.9  685.03   369.7  687.94   389.1   694.1   408.6  700.76   437.8  711.36
   447.5     715   486.4  729.73   496.1   733.5   505.9  737.52   515.6  741.74
#Mann= 3 , 0 , 0
       0     .06       0   281.2    .045       0   296.2      .1       0
Bank Sta=281.2,296.2
XS Rating Curve= 0 ,0
Exp/Cntr=0.3,0.1

Type RM Length L Ch R = 1 ,5317.2  ,604.8,612.3,619.8
XS GIS Cut Line= 3
     1825867.059      596464.909     1825775.029      596249.388
     1825360.824      596366.631
#Sta/Elev= 30
       0  735.27     9.8  733.79    29.3  730.12    39.1   728.6    58.6  724.44
    68.4  722.62    87.9  717.28   107.4  711.34   117.2  708.81   126.9  705.79
   156.2  697.78   175.8  692.86   214.8  684.08   234.4  678.74   244.1  677.35
   263.7  672.61   273.5  670.84   283.3  669.96     342  668.06   346.6  668.14
   361.6  668.53   449.6  671.66   459.4   672.1   469.2  673.35   478.9   676.3
   508.3  689.48   547.4  706.42     567  714.15   586.6   720.9   664.8  746.44
#Mann= 3 , 0 , 0
       0     .08       0   346.6    .045       0   361.6      .1       0
Bank Sta=346.6,361.6
XS Rating Curve= 0 ,0
Exp/Cntr=0.3,0.1

Type RM Length L Ch R = 1 ,4704.5  ,350.7,363.7,376.8
XS GIS Cut Line= 2
     1826130.421      595819.247     1825303.623      595751.726
#Sta/Elev= 30
       0  724.48     9.8  722.76    29.3  719.96    68.3   713.6    78.1  712.23
    87.8  710.99   146.4  704.57   175.7  700.54   185.4  699.66     205  698.71
   234.2  697.78   253.7  697.52   263.5   697.1   341.6  689.24   419.6  680.57
   448.9  677.54   468.4  675.72     488  674.17   517.2  672.44   561.3  667.45
     566  666.95   575.8   666.5   576.3  666.55   585.6  667.53   595.3  670.91
   634.4  690.47   673.4  710.67   741.7  745.25   790.5  769.66   829.6  788.77
#Mann= 3 , 0 , 0
       0     .08       0   561.3    .045       0   576.3      .1       0
Bank Sta=561.3,576.3
XS Rating Curve= 0 ,0
Exp/Cntr=0.3,0.1

Type RM Length L Ch R = 1 ,4340.8  ,361.5,351.1,340.6
XS GIS Cut Line= 2
     1825962.004      595631.281     1825500.986      595284.491
#Sta/Elev= 30
       0  745.55    19.6  738.88    48.9  728.35   107.6  707.94   136.9  697.12
     176  681.82   185.8  678.38   205.3  672.38   215.1  669.76   224.9  667.51
   234.7  665.74   244.4  664.64   248.7  664.46   254.2  664.24   263.7  664.65
   273.8  665.83   283.6  667.48   293.3   669.8   303.1  672.58   312.9  675.03
   332.4  679.28     352  683.05   420.4  695.32     440  699.29   459.6   703.7
   488.9   711.2     528  722.37   547.6  728.59   567.1  735.41   576.9  739.07
#Mann= 3 , 0 , 0
       0     .08       0   248.7    .045       0   263.7      .1       0
Bank Sta=248.7,263.7
XS Rating Curve= 0 ,0
Exp/Cntr=0.3,0.1

Type RM Length L Ch R = 1 ,3988.6  ,452.4,461.4,470.4
XS GIS Cut Line= 2
     1826215.039      595250.243     1825372.332      595089.859
#Sta/Elev= 30
       0   845.7    29.2  843.88    48.7  842.01    58.5  840.09    68.2   836.8
      78  832.42   107.2  817.37   126.7  807.79   146.2  798.86     195  779.51
   282.7  739.44   331.4   718.3   360.7  706.14   399.7  691.22   409.4  687.79
   419.2  685.29   428.9  683.42   497.2  671.36   526.4  665.73   529.3  665.39
   536.2  664.58   544.3   665.1   545.9   665.2   555.6  668.11   604.4  691.55
   643.4  710.78   692.1  733.49   701.9  738.34   760.4  769.12   857.8  818.17
#Mann= 3 , 0 , 0
       0      .1       0   529.3    .045       0   544.3      .1       0
Bank Sta=529.3,544.3
XS Rating Curve= 0 ,0
Exp/Cntr=0.3,0.1