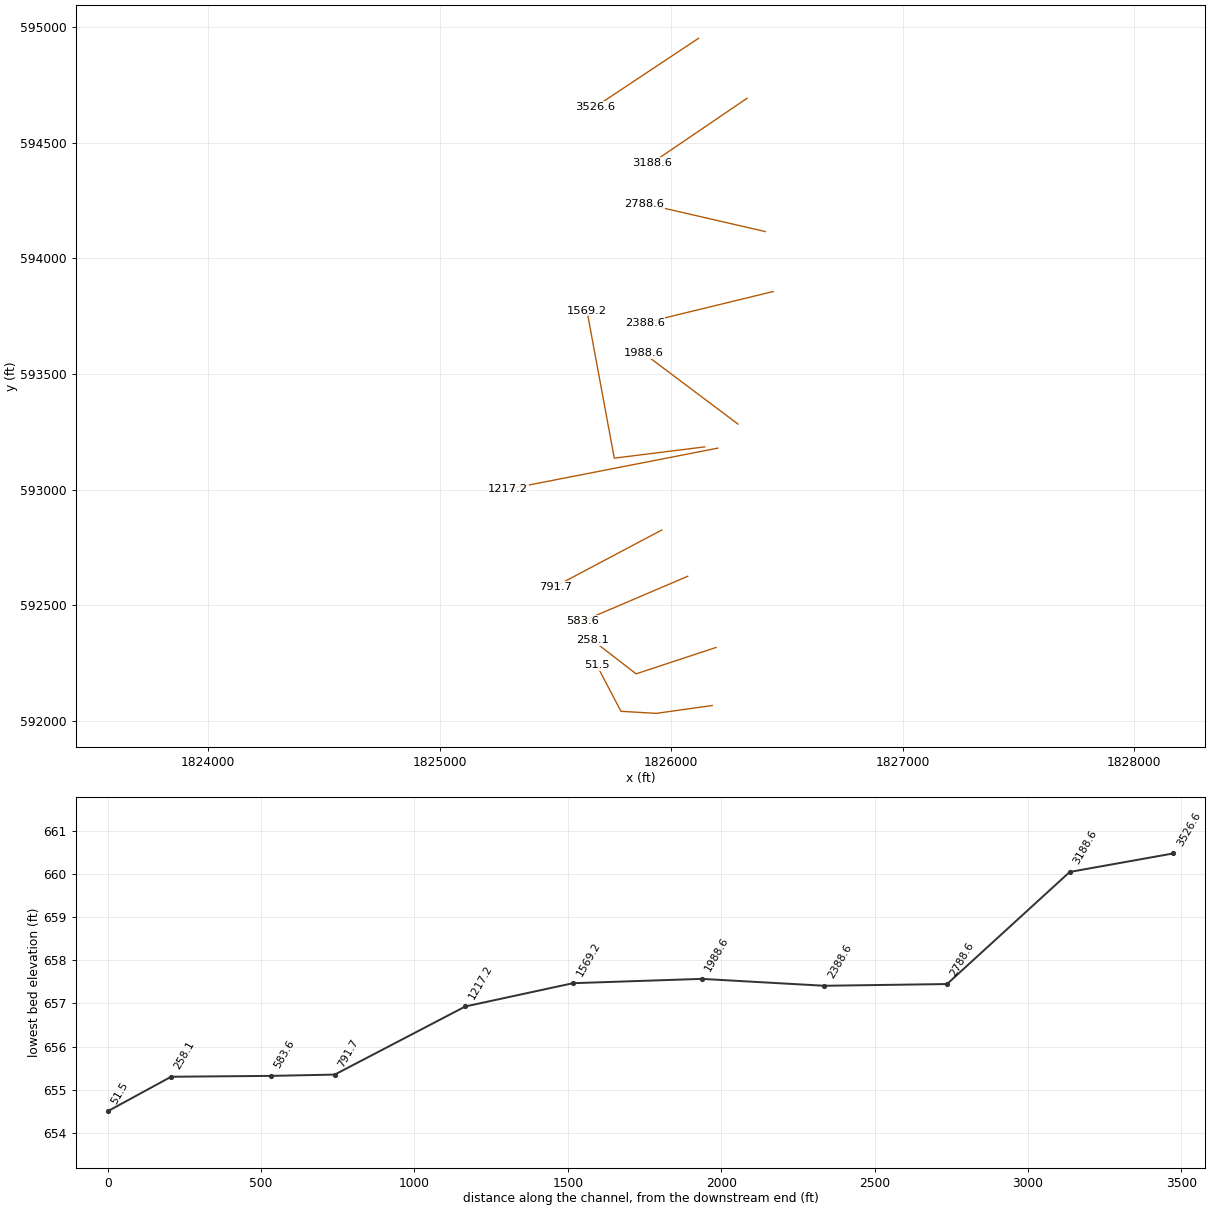
HEC-RAS study WolfCreek.prj: WolfCreek

--- WolfCreek.g01 (geometry) --- (continued)

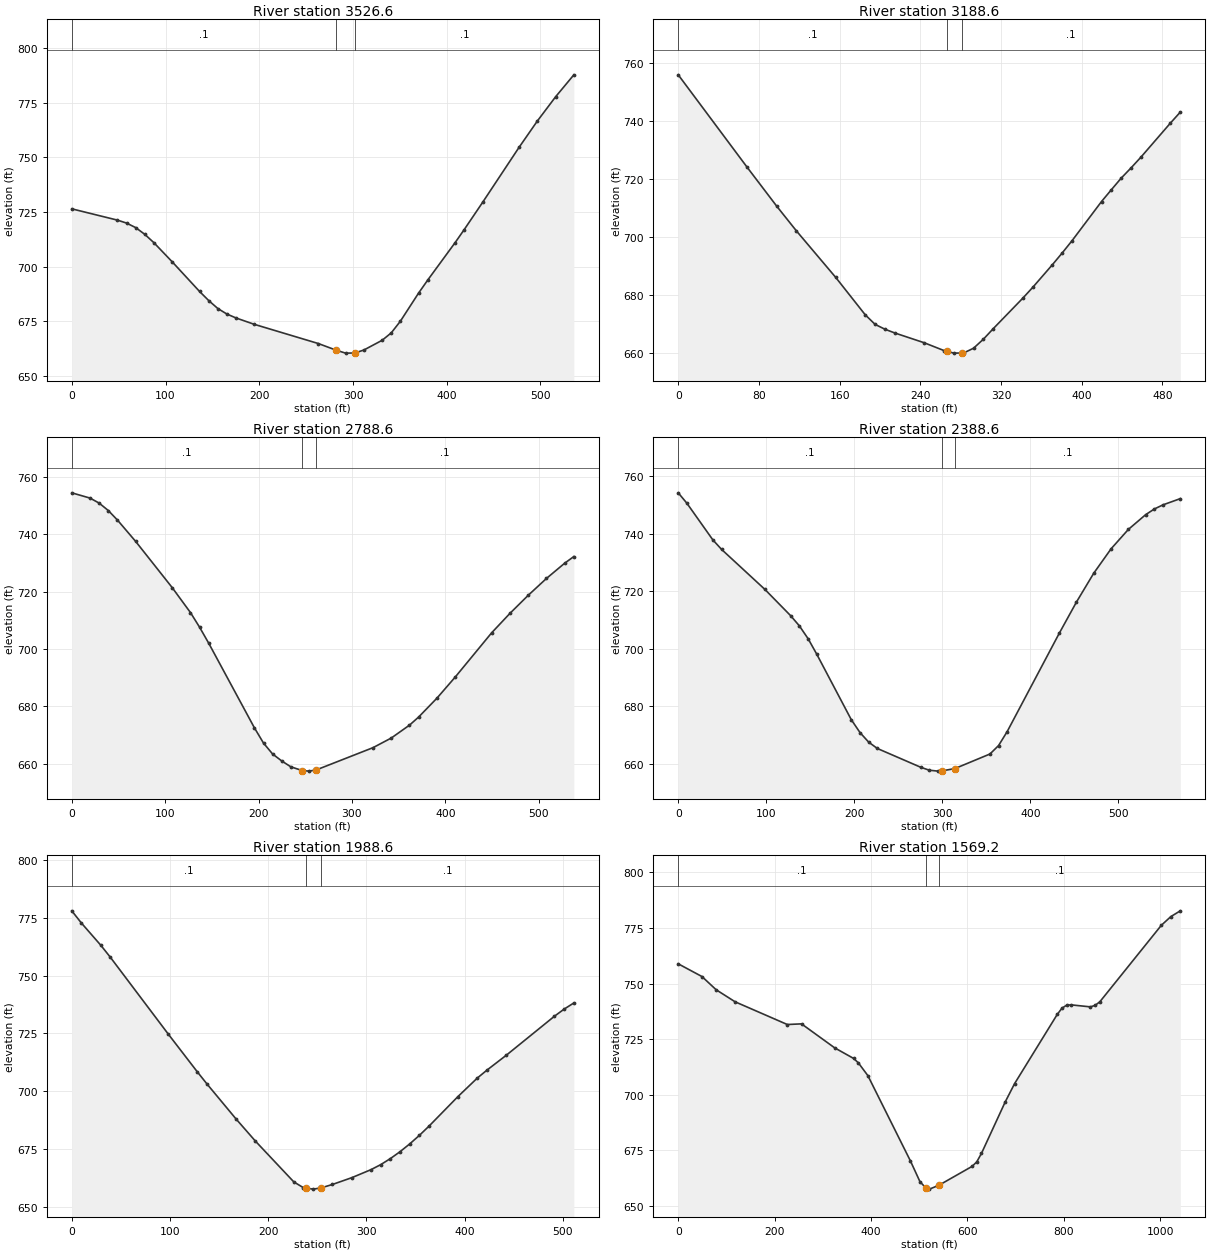
Type RM Length L Ch R = 1 ,3526.6  ,337.9,338.2,338.5
XS GIS Cut Line= 2
     1826117.761       594952.29     1825671.842       594655.69
#Sta/Elev= 30
       0  726.43    48.7  721.27    58.4  719.93    68.2  717.85    77.9  714.77
    87.6  710.96   107.1  702.23   136.3  688.68   146.1   684.5   155.8  680.87
   165.5  678.34   175.3  676.54   194.8  673.63   262.9  664.88   282.4  661.77
   292.1  660.48   301.9  660.54   311.6   661.9   331.1  666.35   340.8  669.73
   350.5  675.04     370  687.94   379.8  693.92     409  711.02   418.7  716.98
   438.2  729.34   477.1   754.5   496.6  766.53   516.1  777.62   535.6  787.68
#Mann= 3 , 0 , 0
       0      .1       0   282.4    .045       0   301.9      .1       0
Bank Sta=282.4,301.9
XS Rating Curve= 0 ,0
Exp/Cntr=0.3,0.1

Type RM Length L Ch R = 1 ,3188.6  ,418.7,400,381.3
XS GIS Cut Line= 2
      1826327.33      594692.941     1825915.943      594412.715
#Sta/Elev= 30
       0  755.99    68.3  724.13    97.6  710.73   117.1  702.22   156.2  686.13
   185.4  673.26   195.2  669.96     205  668.28   214.7     667     244  663.61
   263.5  660.93   266.2  660.69   273.3  660.05   281.2   660.1     283  660.11
   292.8  661.74   302.6  664.87   312.3  668.47   341.6  678.98   351.4  682.69
   370.9   690.5   380.6  694.54   390.4  698.78   419.7  712.32   429.4  716.36
   439.2  720.38     449  723.92   458.7  727.59     488  739.36   497.8  743.14
#Mann= 3 , 0 , 0
       0      .1       0   266.2    .045       0   281.2      .1       0
Bank Sta=266.2,281.2
XS Rating Curve= 0 ,0
Exp/Cntr=0.3,0.1

Type RM Length L Ch R = 1 ,2788.6  ,389.6,400,410.4
XS GIS Cut Line= 2
     1826405.821      594116.251     1825882.038      594237.252
#Sta/Elev= 30
       0   754.5    19.6  752.66    29.3  750.92    39.1  748.33    48.9  745.01
    68.4  737.56   107.5  721.46   127.1  712.74   136.8  707.67   146.6  702.08
   195.5  672.59   205.3  667.23     215  663.44   224.8     661   234.6  658.95
   246.7  657.66   254.1  657.45   261.7  657.86   322.6  665.64   342.1  668.99
   361.6  673.48   371.4  676.31     391  682.89   410.5  690.22   449.6  705.69
   469.2  712.47   488.7  718.75   508.3  724.65   527.8  729.96   537.6  732.28
#Mann= 3 , 0 , 0
       0      .1       0   246.7    .045       0   261.7      .1       0
Bank Sta=246.7,261.7
XS Rating Curve= 0 ,0
Exp/Cntr=0.3,0.1

Type RM Length L Ch R = 1 ,2388.6  ,419.7,400,380.2
XS GIS Cut Line= 2
     1826439.844      593856.632     1825885.815      593721.612
#Sta/Elev= 30
       0   754.3     9.8  750.69    39.3  737.92    49.2  734.61    98.3  720.71
   127.8  711.48   137.6  707.97   147.5  703.51   157.3  698.13   196.6  675.28
   206.5  670.81   216.3   667.5   226.1   665.3   275.3  658.77   285.1  657.73
     295  657.41   299.1  657.48   314.1  658.29     354  663.37   363.8  666.31
   373.6  671.19   432.6  705.34   452.3   716.3   471.9  726.32   491.6  734.82
   511.2  741.56   530.9  746.71   540.8  748.69   550.6  750.12   570.2  752.28
#Mann= 3 , 0 , 0
       0      .1       0   299.1    .045       0   314.1      .1       0
Bank Sta=299.1,314.1
XS Rating Curve= 0 ,0
Exp/Cntr=0.3,0.1

Type RM Length L Ch R = 1 ,1988.6  ,436.1,419.3,402.5
XS GIS Cut Line= 2
     1826288.047      593283.176     1825879.624      593590.544
#Sta/Elev= 30
       0   778.1     9.8  772.82    29.5  763.22    39.3  757.98    98.3  724.69
   127.8  708.38   137.6  703.15   167.1  688.04   186.8  678.45   226.1  660.69
   235.9  658.18   238.8     658   245.8  657.57   253.8  658.09   265.4  659.59
   285.1  662.53   304.7  666.01   314.6  668.19   324.4  670.79   334.2  673.77
     344  677.12   353.9  680.84   363.7  684.84   393.2  697.66   412.9  705.67
   422.7   709.1   442.4  715.55   491.5  732.47   501.3  735.53   511.2   738.2
#Mann= 3 , 0 , 0
       0      .1       0   238.8    .045       0   253.8      .1       0
Bank Sta=238.8,253.8
XS Rating Curve= 0 ,0
Exp/Cntr=0.3,0.1

Type RM Length L Ch R = 1 ,1569.2  ,315.6,351.3,387.1
XS GIS Cut Line= 3
     1826144.465      593184.464     1825754.021      593135.608
     1825636.057      593773.109
#Sta/Elev= 30
       0  758.86    49.2  753.14    78.7  747.19     118  741.77   226.3  731.55
   255.8  731.84   324.6  721.05     364  716.27   373.8  714.28   393.5  708.54
   481.9  670.11   501.5  660.86   513.6  658.04   521.2  657.47   540.8   659.2
   609.6  667.69   619.4  669.72   629.2  673.55   678.4  696.68     698  704.97
   786.4  736.08   796.2   738.9   806.1  740.26   815.9  740.38   855.2  739.49
     865  740.17   874.8  741.77  1002.5  776.22  1022.2  780.12  1041.8  782.71
#Mann= 3 , 0 , 0
       0      .1       0   513.6    .045       0   540.8      .1       0
Bank Sta=513.6,540.8
XS Rating Curve= 0 ,0
Exp/Cntr=0.3,0.1

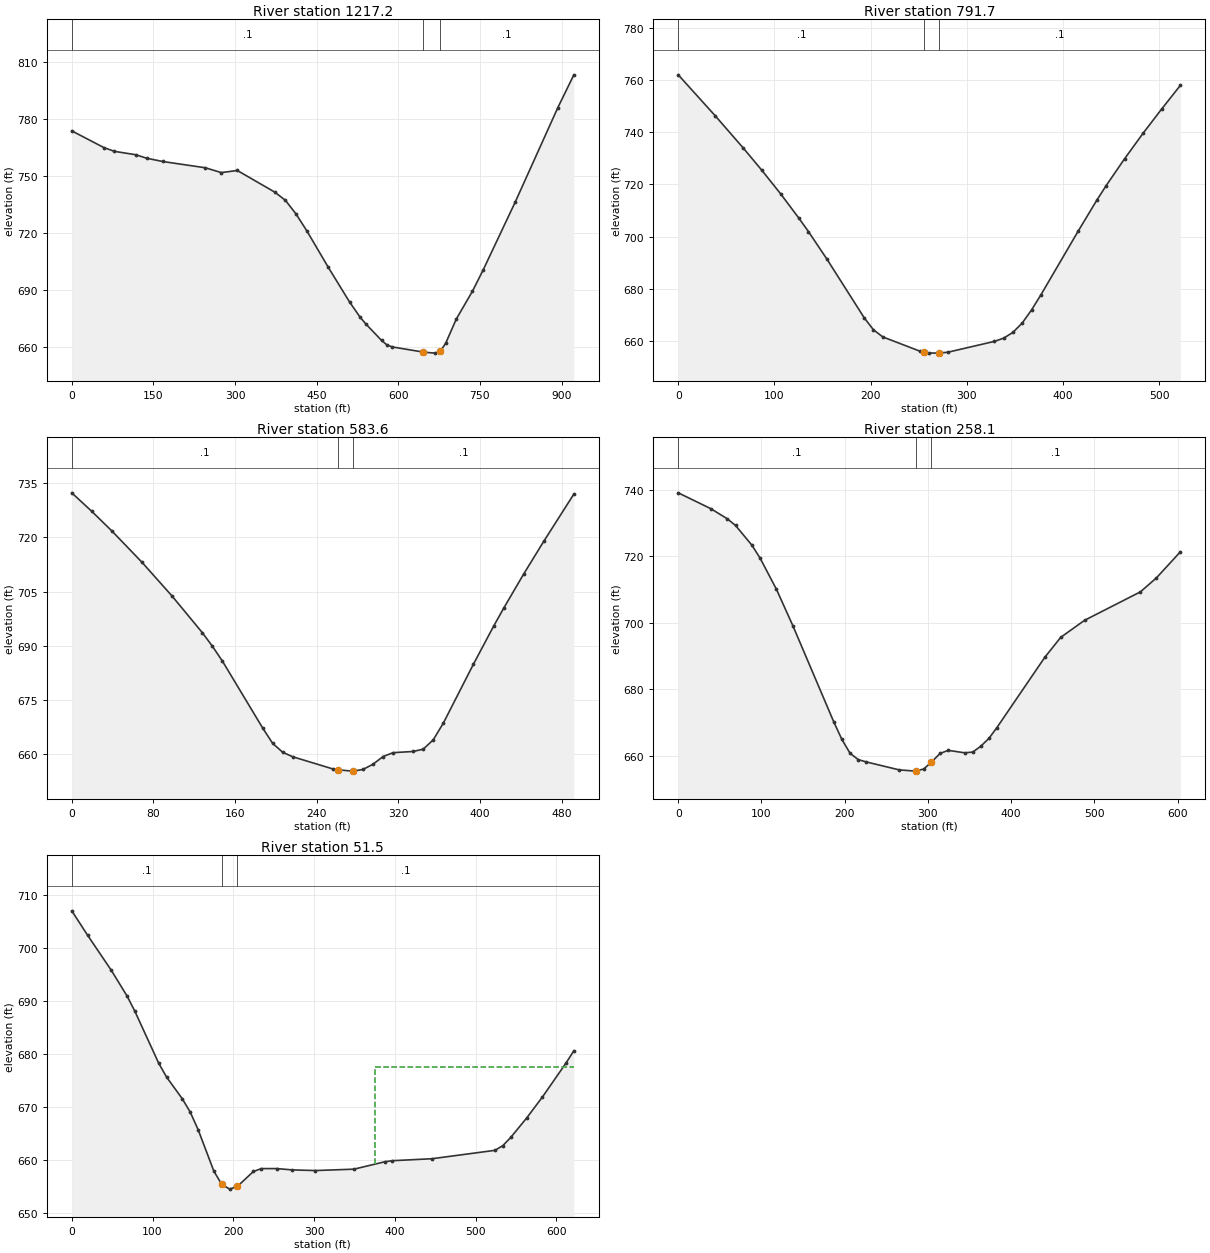
Type RM Length L Ch R = 1 ,1217.2  ,419.1,425.7,432.3
XS GIS Cut Line= 2
     1826200.851       593178.94     1825295.521      593001.945
#Sta/Elev= 30
       0  773.94    58.9  765.14    78.5  763.14   117.8  761.36   137.4  759.55
   166.8  757.81   245.3  754.51   274.8  751.96   304.2  753.07   372.9   741.7
   392.5  737.38   412.2  730.12   431.8  721.34     471  702.25   510.3  683.91
   529.9  675.81   539.7  672.49   569.2   663.6     579  661.29   588.8   660.2
   646.2  657.46   667.3  656.93   677.1  657.88     687  662.11   706.6  674.93
     736  689.41   755.6  700.55   814.5  736.27     893  786.12   922.5  803.43
#Mann= 3 , 0 , 0
       0      .1       0   646.2    .045       0   677.1      .1       0
Bank Sta=646.2,677.1
XS Rating Curve= 0 ,0
Exp/Cntr=0.3,0.1

Type RM Length L Ch R = 1 ,791.7   ,209.9,208,206.1
XS GIS Cut Line= 2
     1825959.318       592824.86     1825498.146      592580.147
#Sta/Elev= 30
       0  761.98    38.7  746.19    67.7   733.9      87  725.38   106.4  716.42
   125.7  706.94   135.4  701.93   154.7  691.32   193.4  668.88     203  664.29
   212.7  661.56   251.4  656.09   255.9  655.77     261  655.41   270.7  655.35
   270.9  655.36   280.4   655.7   328.7  659.84   338.4  661.08     348  663.29
   357.7  666.88   367.4   671.9   377.1  677.66   415.7  701.98   435.1  713.84
   444.7  719.37   464.1   729.8   483.4   739.6   502.7  748.88   522.1  757.92
#Mann= 3 , 0 , 0
       0      .1       0   255.9    .045       0   270.9      .1       0
Bank Sta=255.9,270.9
XS Rating Curve= 0 ,0
Exp/Cntr=0.3,0.1

Type RM Length L Ch R = 1 ,583.6   ,327.5,325.5,323.5
XS GIS Cut Line= 2
     1826071.179      592624.686     1825619.057      592431.116
#Sta/Elev= 30
       0  732.35    19.7   727.2    39.4  721.76    68.8  713.12    98.4  703.73
   127.9  693.64   137.7  689.91   147.6  685.76   186.9   667.3   196.7  663.03
   206.6  660.54   216.4   659.3   255.7  655.93   260.8  655.67   275.4  655.32
   275.8  655.34   285.2  655.78   295.1  657.23   304.9  659.36   314.8  660.43
   334.4  660.76   344.3  661.41   354.1  663.99   363.9  668.58   393.4   684.9
   413.1  695.38     423  700.38   442.6  709.85   462.3  718.91   491.8     732
#Mann= 3 , 0 , 0
       0      .1       0   260.8    .045       0   275.8      .1       0
Bank Sta=260.8,275.8
XS Rating Curve= 0 ,0
Exp/Cntr=0.3,0.1

Type RM Length L Ch R = 1 ,258.1   ,210.7,206.6,202.5
XS GIS Cut Line= 3
     1826193.486      592316.623     1825848.192      592202.376
     1825658.801      592348.985
#Sta/Elev= 30
       0  739.12    39.3  734.33      59  731.29    68.8   729.3    88.5  723.36
    98.3  719.47     118  710.06   137.6  699.16   186.8  670.17   196.6  664.85
   206.4  660.69   216.3  658.76   226.1  658.06   265.4  655.68   285.1   655.3
   294.9  655.94   304.2  658.02   314.6  660.63   324.4  661.56     344  660.82
   353.9  661.04   363.7  662.85   373.3  665.17   382.9  668.43   440.4  689.58
   459.5  695.59   488.2  700.73   555.3   709.3   574.5   713.5   603.2  721.34
#Mann= 3 , 0 , 0
       0      .1       0   285.1    .045       0   304.2      .1       0
Bank Sta=285.1,304.2
XS Rating Curve= 0 ,0
Exp/Cntr=0.3,0.1

Type RM Length L Ch R = 1 ,51.5    ,56.2,51.5,46.7
XS GIS Cut Line= 4
     1826177.208      592065.378      1825935.21      592031.319
      1825782.84      592040.282     1825678.871      592239.259
#Sta/Elev= 30
       0  707.07    19.6  702.46    48.9  695.84    68.4  690.99    78.2  688.07
   107.5  678.32   117.3  675.68   136.8  671.57   146.6  669.06   156.4  665.74
     176  657.86   185.7  655.39   195.5   654.5     205  655.01   224.8  657.83
   234.6  658.38   253.9  658.38     273  658.13   301.6  658.01   349.3  658.27
   387.5  659.67     397  659.87   445.8  660.24   523.9  661.83   533.7  662.73
   543.4  664.27     563  667.92   582.5  671.88   611.8  678.32   621.5  680.63
#Mann= 3 , 0 , 0
       0      .1       0   185.7    .045       0     205      .1       0
#XS Ineff= 2 , 0
                          375.56          677.64
Permanent Ineff=
       F       F
Bank Sta=185.7,205
XS Rating Curve= 0 ,0
Exp/Cntr=0.3,0.1

Chan Stop Cuts=-1
Use User Specified Reach Order=0
Composite Channel Slope=5